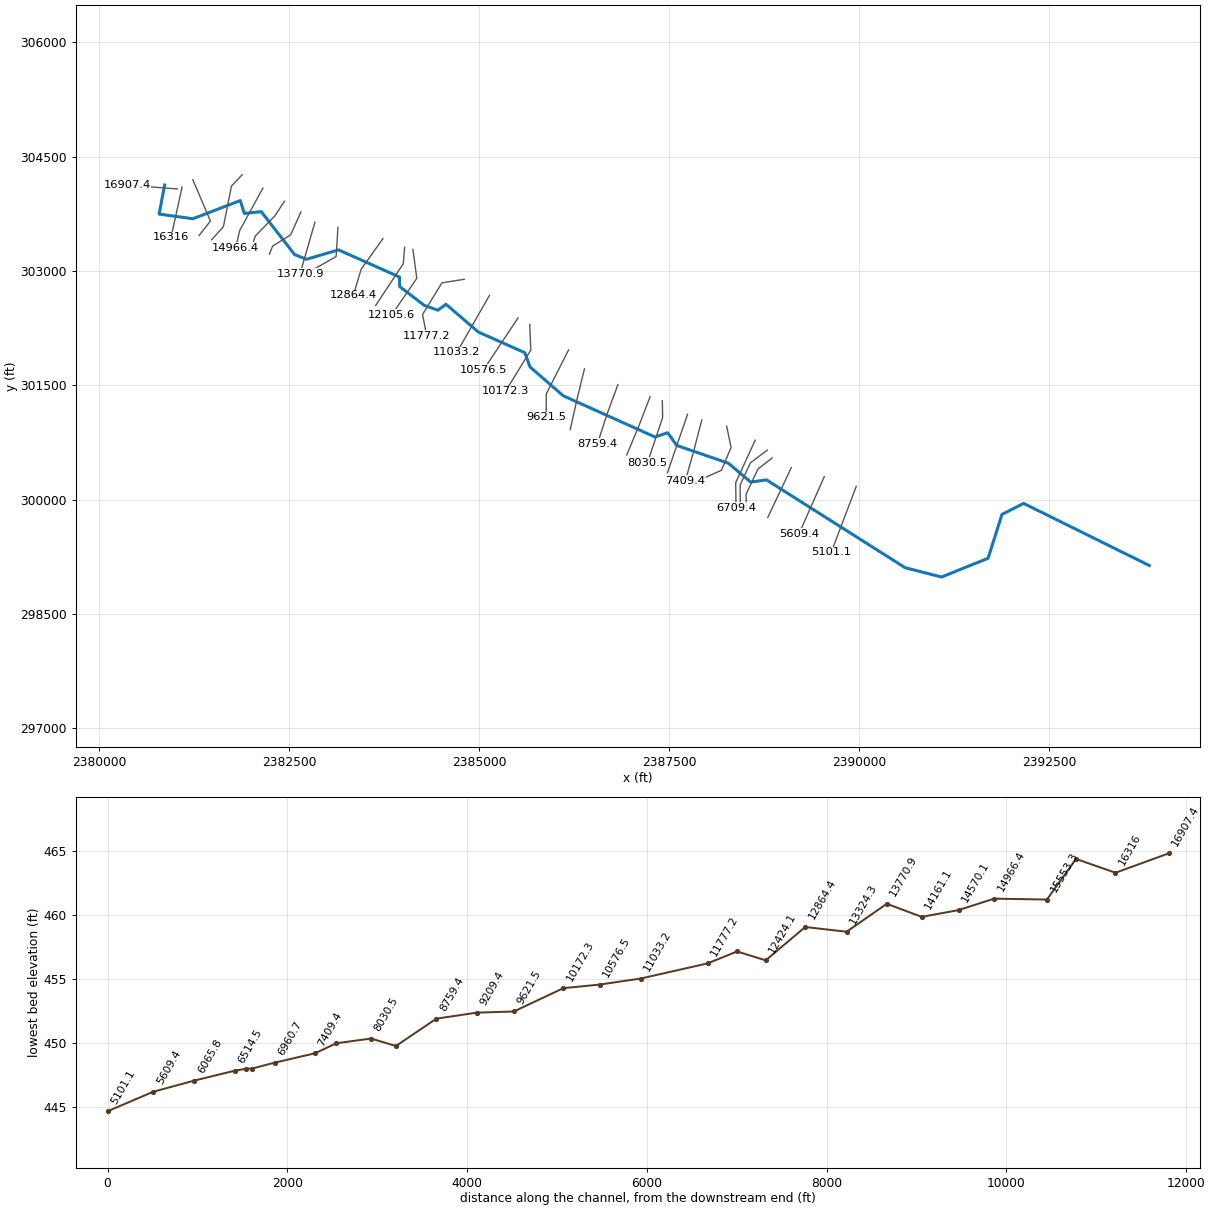
--- MILLCREEK2.prj (project) ---

Proj Title=MILLCREEK2
Current Plan=p01
Default Exp/Contr=0,0
English Units
Geom File=g01
Flow File=f01
Plan File=p01
BEGIN DESCRIPTION:
END DESCRIPTION:
DSS Export Rating Curves= 0
DSS Export Rating Curve Sorted= 0
DSS Export Volume Flow Curves= 0
DXF OffsetX= 0
DXF OffsetY= 0
DXF ScaleX= 0
DXF ScaleY= 0

--- MILLCREEK2.p01 (plan) ---

Plan Title=Floodplain
Program Version=4.00
Geom File=g01
Flow File=f01
K Sum by GR=0
Std Step Tol=0.01
Critical Tol=0.01
Num of Std Step Trials=20
Max Error Tol=0.3
Flow Tol Ratio=0.001
Split Flow NTrial=30
Split Flow Tol=0.02
Split Flow Ratio=0.02
Log Output Level=0
Friction Slope Method=1
Unsteady Friction Slope Method=2
Unsteady Bridges Friction Slope Method=1
Global Log Level=0
CheckData=False
Run HTab=0
Run UNet=0
Run PostProcess=0
UNET Theta=0
UNET Theta Warmup=0
UNET ZTol=0
UNET ZSATol=0
UNET MxIter=0
UNET MaxInSteps=0
UNET DtIC=0
UNET DtMin=0
UNET MaxCRTS=0
UNET WFStab=0
UNET SFStab=0
UNET WFX=0
UNET SFX=0
UNET DSS MLevel=0
UNET DZMax Abort=0
UNET Convert EG Bridges=0
UNET Use Existing IB Tables=0
UNET Froude Limit=0
UNET Froude Power=0
Write IC File=0
Echo Input=False
Echo Output=False
Write Detailed=0

--- MILLCREEK2.f01 (steady flow) ---

Flow Title=NFF Regression Equation
Program Version=5.03
Number of Profiles= 1
Profile Names=P100yr
River Rch & RM=MILLCREEK2,Main            ,16907.4
4517.649
River Rch & RM=MILLCREEK2,Main            ,12864.4
4561.653
River Rch & RM=MILLCREEK2,Main            ,12424.1
5733.296
River Rch & RM=MILLCREEK2,Main            ,3142.8
5984.828
River Rch & RM=MILLCREEK2,Main            ,3142.8
5983.121
Boundary for River Rch & Prof#=MILLCREEK2,Main            , 1
Up Type= 0
Dn Type= 3
Dn Slope=0.005222
Set Internal Change=MILLCREEK2      ,Main            ,16316   , 1 , 3 ,475
DSS Import GetInterval= 0
DSS Import GetPeak= 0
DSS Import FillOption= 0

--- MILLCREEK2.g01 (geometry) ---

Geom Title=USGS 10m DEM
Program Version=4.10

River Reach=MILLCREEK2      ,Main
Reach XY= 30
     2380857.852      304126.744     2380784.583      303745.104
      2381228.16      303683.472     2381852.379      303922.039
      2381907.24      303753.289     2382129.161      303776.831
     2382568.166      303213.637     2382724.416      303151.831
     2383145.944      303275.442     2383949.245      302918.722
     2383950.729      302794.525     2384273.646      302547.997
     2384454.201      302483.761     2384560.104      302561.886
     2384987.188      302197.303     2385598.299       301926.47
     2385666.785      301739.494     2386105.243      301360.497
      2387311.84      300820.567     2387478.507      300876.122
     2387598.299      300709.456     2388277.118      300476.817
     2388572.257      300228.553     2388778.854      300258.067
     2390605.243      299105.289      2391084.41      298983.761
     2391696.015      299229.616     2391878.845      299804.734
     2392163.859      299949.266     2393818.304        299134.3

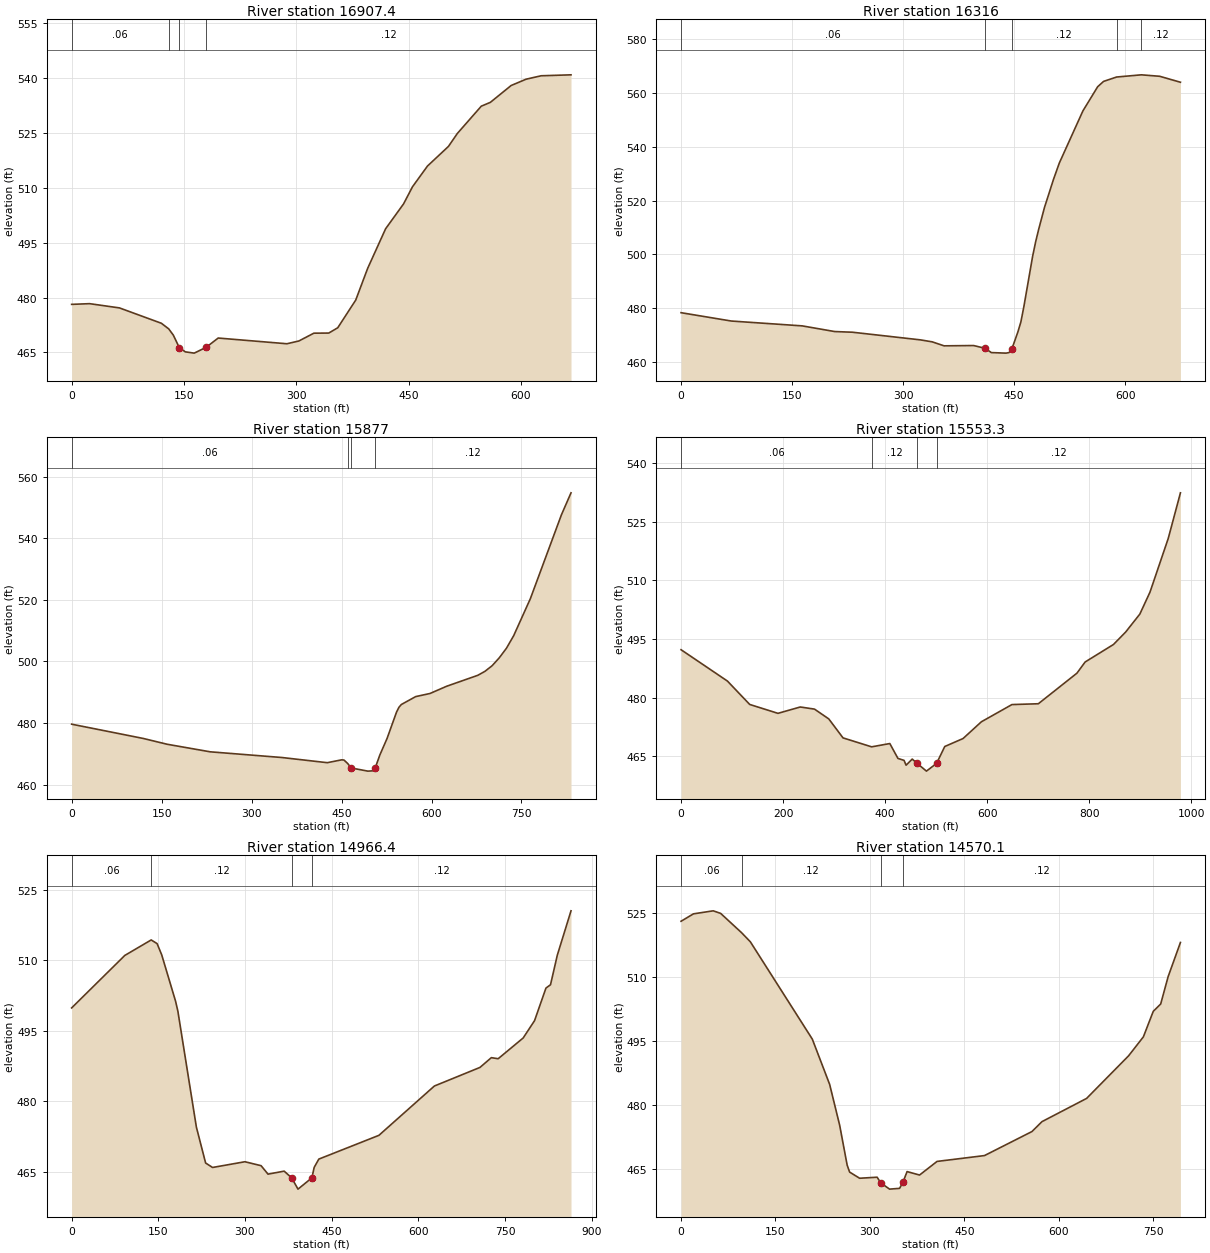
Type RM Length L Ch R = 1 ,16907.4 ,558.8,591.4,624.1
XS GIS Cut Line= 2
     2381025.812      304074.655     2380360.873      304125.526
#Sta/Elev= 30
       0  478.13      24  478.32    63.9  477.16   119.8  472.97  129.67471.4313
   135.8  469.73   143.8   466.3   151.8  465.16   163.7  464.81   179.7   466.4
   195.7  468.93   287.5  467.37   303.5  468.13   323.5  470.26   343.4  470.29
   355.4  471.74   379.4   479.3   395.3  487.95   419.3  498.78   443.3  505.58
   455.2  510.25   475.2  515.91   503.2  521.27   515.1  524.81   547.1  532.27
   559.1   533.3     587  537.92     607  539.64     627  540.57   666.9  540.83
#Mann= 4 ,-1 , 0
       0     .06       0  129.67     .12       0   143.8    .045       0
   179.7     .12       0
Bank Sta=143.8,179.7
XS Rating Curve= 0 ,0
Exp/Cntr=0.3,0.1

Type RM Length L Ch R = 1 ,16316   ,424.6,439,452.8
XS GIS Cut Line= 2
     2381086.576       304098.96      2380942.47      303439.762
#Sta/Elev= 30
       0  478.33    67.9  475.23   163.7  473.43   207.6  471.32   231.6  471.07
   323.4  468.23   339.4  467.49   355.4  466.01   395.3  466.12   411.2  465.07
   419.2   463.5   439.2   463.3   443.2  463.51   447.2  464.99   455.2  471.22
   459.2  474.91   463.2  480.56   475.1  499.35   479.1  504.63   483.1  509.18
   491.1  517.47   503.1  527.76   511.1  533.95     543  553.34     563  562.35
     571  564.32  588.49565.9373  622.03566.7557   646.8  566.21   674.8     564
#Mann= 5 ,-1 , 0
       0     .06       0   411.2    .045       0   447.2     .12       0
  588.49    .016       0  622.03     .12       0
Bank Sta=411.2,447.2
XS Rating Curve= 0 ,0
Exp/Cntr=0.3,0.1

Type RM Length L Ch R = 1 ,15877   ,339.2,323.7,306.3
XS GIS Cut Line= 3
     2381228.251      304195.716     2381460.626      303653.902
     2381310.071       303463.13
#Sta/Elev= 30
       0  479.62   119.5  474.98   159.3   473.1     231  470.65   350.5   468.8
   426.2  467.12   450.1  468.04   454.1  467.97  460.37466.8328   466.1   465.4
   493.9  464.38   501.9  464.47   505.9  465.28   513.9  469.63   525.8  474.93
   541.7  483.54   545.7   485.1   549.7     486   573.6  488.57   597.5  489.58
   625.4  491.94   677.2  495.48   689.1  496.77   701.1   498.6     713  501.16
     725  504.28     737  508.34   764.8  520.34   816.6  547.57   832.6  554.71
#Mann= 4 ,-1 , 0
       0     .06       0  460.37     .12       0   466.1    .045       0
   505.9     .12       0
Bank Sta=466.1,505.9
XS Rating Curve= 0 ,0
Exp/Cntr=0.3,0.1

Type RM Length L Ch R = 1 ,15553.3 ,594.5,587,576.2
XS GIS Cut Line= 4
     2381878.124      304261.473     2381736.893      304111.786
     2381630.894       303579.62     2381476.306      303408.441
#Sta/Elev= 30
       0  492.24      91  484.22   134.6  478.25     190  475.98   233.7   477.6
   261.6  477.06   289.6  474.56   317.5  469.71  373.67467.4153   409.3  468.26
   425.2  464.46   437.2  463.96   441.2  462.73   453.2  464.29  463.09463.1684
   481.1  461.21     501  463.19     517   467.5   552.9  469.54   588.8  473.82
   648.7  478.22   700.5  478.43   776.2  486.25   792.2   489.1   847.8  493.58
   871.7  496.76   899.5  501.35   919.4  506.96   955.2  520.69   979.1  532.34
#Mann= 4 ,-1 , 0
       0     .06       0  373.67     .12       0  463.09    .045       0
     501     .12       0
Bank Sta=463.09,501
XS Rating Curve= 0 ,0
Exp/Cntr=0.3,0.1

Type RM Length L Ch R = 1 ,14966.4 ,402.6,396.2,379.9
XS GIS Cut Line= 3
     2382150.962      304085.761     2381844.926      303528.521
     2381793.691      303305.811
#Sta/Elev= 30
       0  499.86      92  511.03  137.68514.3298   147.9  513.55   155.9  511.16
   179.9  501.28   183.9  499.15   215.9  474.49   231.9  466.84   243.9  465.89
   299.9  467.11   327.9  466.27   339.9  464.47   367.8  465.11  380.67463.7042
   391.8  461.28   415.8  463.68   419.8  465.91   427.8  467.67   531.8  472.73
   627.8  483.23   706.7  487.19   726.4  489.27   738.2  489.04   781.5  493.46
   801.2  497.15   820.9  504.08   828.8  504.79   840.6   511.1   864.3  520.53
#Mann= 4 ,-1 , 0
       0     .06       0  137.68     .12       0  380.67    .045       0
   415.8     .12       0
Bank Sta=380.67,415.8
XS Rating Curve= 0 ,0
Exp/Cntr=0.3,0.1

Type RM Length L Ch R = 1 ,14570.1 ,404.2,409,381.6
XS GIS Cut Line= 4
     2382434.716      303914.217     2382310.195      303723.037
      2382049.94      303455.864      2381992.81      303272.307
#Sta/Elev= 30
       0  523.15    19.7  524.88    51.1  525.59    62.9  524.99   96.22 520.456
   110.1  518.33   208.5  495.54   236.1  484.92     252  475.35   263.9  466.01
   267.8  464.38   283.7  462.94   311.5  463.18   317.4 461.825   331.3  460.39
   347.2  460.57   352.4461.9646   359.1   464.5   378.9  463.69   406.7  466.88
   482.1  468.25   557.5  473.88   573.4   476.2   644.3  481.64     711  491.62
   734.5  496.06   750.2  502.04     762  503.76   773.8  510.15   793.4  518.18
#Mann= 4 ,-1 , 0
       0     .06       0   96.22     .12       0   317.4    .045       0
   352.4     .12       0
Bank Sta=317.4,352.4
XS Rating Curve= 0 ,0
Exp/Cntr=0.3,0.1

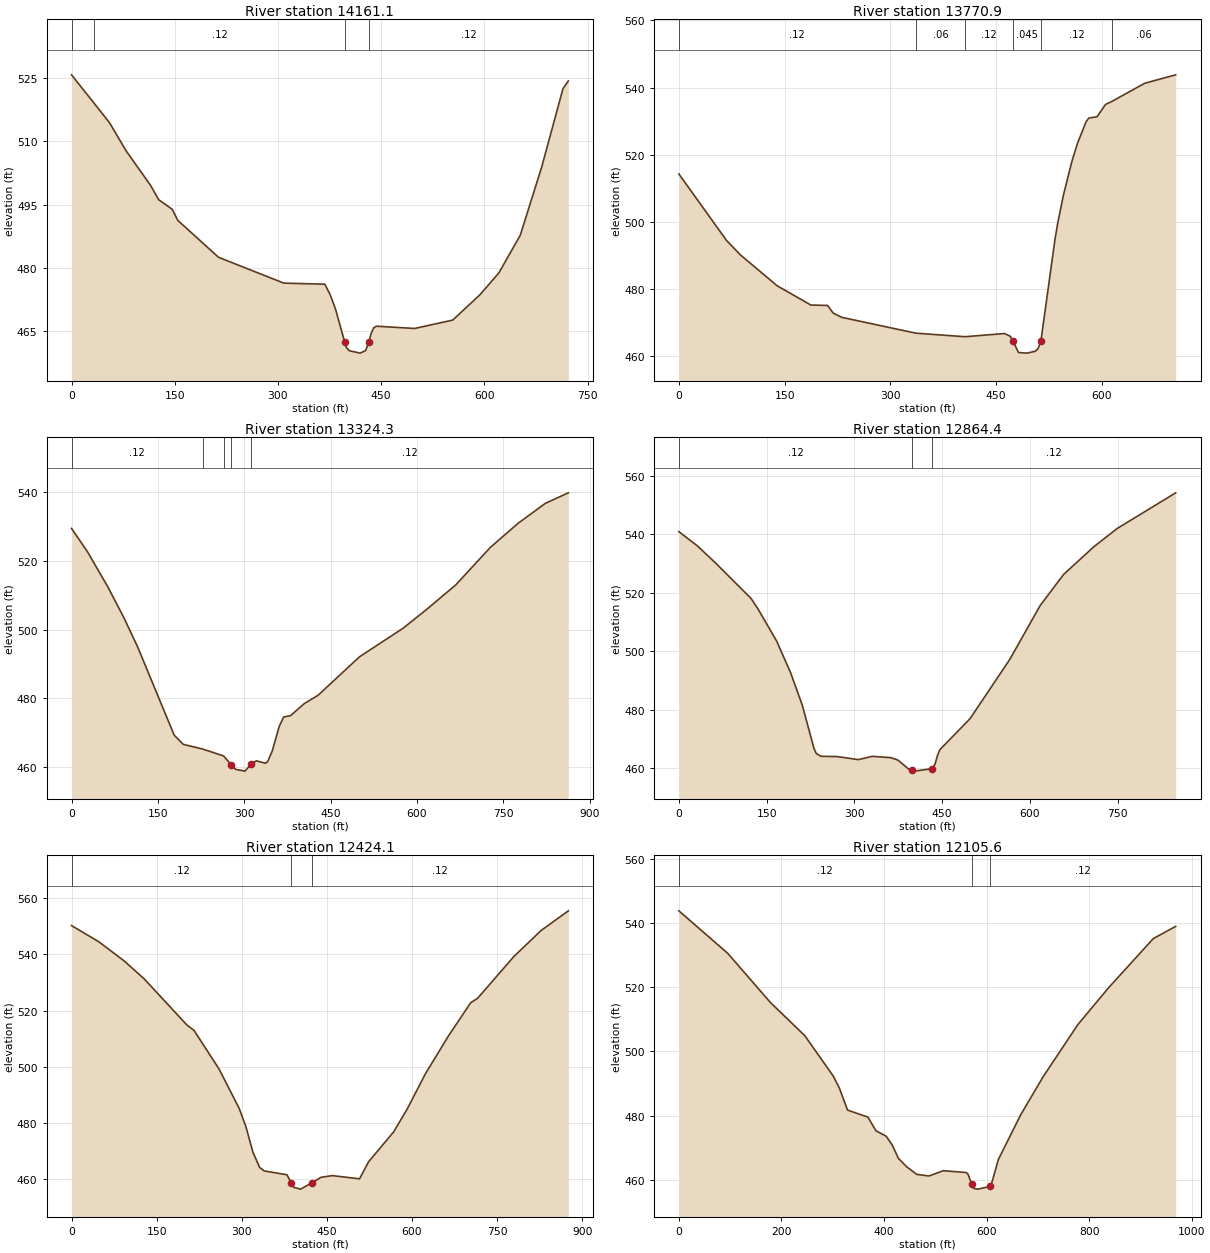
Type RM Length L Ch R = 1 ,14161.1 ,371.4,390.3,408.2
XS GIS Cut Line= 4
     2382651.231      303772.372     2382516.331      303472.853
      2382278.27       303323.69     2382236.484      303219.098
#Sta/Elev= 30
       0  525.79   33.05519.0239    55.4  514.41    79.2  507.82   114.8  499.63
   126.6  496.22   146.4  493.93   154.4  491.32   213.7  482.56   308.7  476.44
   368.1  476.19     376  473.71   383.9  470.19  397.21462.3914   399.7  461.14
   403.7  460.43   419.5  459.86   427.4  460.46  432.13462.4261   435.3  464.45
   439.3  465.86   443.2  466.24   498.6   465.7     554  467.68   593.6  473.68
   621.1  478.86   652.2  487.77   683.2  503.85   714.3  522.51   722.1  524.34
#Mann= 4 ,-1 , 0
       0     .06       0   33.05     .12       0  397.21    .045       0
  432.13     .12       0
Bank Sta=397.21,432.13
XS Rating Curve= 0 ,0
Exp/Cntr=0.3,0.1

Type RM Length L Ch R = 1 ,13770.9 ,441.5,446.6,451.6
XS GIS Cut Line= 2
     2382835.805      303638.826     2382640.197      302961.692
#Sta/Elev= 30
       0  514.26    67.7  494.42    87.6  490.09   139.4  480.95   187.2  475.21
     211  475.08     219  472.79     231  471.55  336.23466.8216  405.84  465.77
   461.9  466.71   469.9  465.94   473.9  464.53   481.8  461.05   493.8  460.88
   505.7  461.44   509.7   462.3   513.7  464.64   533.6  494.82   537.6  499.77
   545.5  507.91   557.5  517.96   565.4  523.33   577.4  529.68   581.4  530.88
   593.3  531.31   605.3  534.96  614.56 535.896     661  541.28   704.8  543.78
#Mann= 6 ,-1 , 0
       0     .12       0  336.23     .06       0  405.84     .12       0
   473.9    .045       0   513.7     .12       0  614.56     .06       0
Bank Sta=473.9,513.7
XS Rating Curve= 0 ,0
Exp/Cntr=0.3,0.1

Type RM Length L Ch R = 1 ,13324.3 ,466.5,459.9,442.2
XS GIS Cut Line= 3
     2383138.407      303568.433     2383115.089      303188.608
     2382696.414      302948.658
#Sta/Elev= 30
       0  529.52    27.8   522.7    63.4  512.37    91.2   503.4     115  494.91
   178.4  469.19   194.2  466.51  227.99465.1373  264.06463.1455   277.5  460.54
   285.2  459.21   301.3   458.7  311.45460.6394   321.1  461.71   336.9     461
   340.9  461.52   348.8  464.62   360.7   471.7   368.6  474.51   380.5  474.89
   404.5  478.41   428.4  480.84   500.2  492.04     576  500.39   615.8  505.72
   667.7  513.06   727.5  523.96   775.4  530.95   823.2  536.83   863.1   539.9
#Mann= 5 ,-1 , 0
       0     .12       0  227.99     .06       0  264.06     .12       0
   277.5    .045       0  311.45     .12       0
Bank Sta=277.5,311.45
XS Rating Curve= 0 ,0
Exp/Cntr=0.3,0.1

Type RM Length L Ch R = 1 ,12864.4 ,440.2,440.3,440.4
XS GIS Cut Line= 3
     2383731.596      303423.719     2383444.058      303021.997
     2383341.501      302681.607
#Sta/Elev= 30
       0  540.93    31.9  536.01    63.7  530.01   123.5  518.07   135.5  514.44
   167.3  503.47   191.2  492.64   211.2  481.51   231.1  466.78   235.1  465.06
     243  464.14   270.9  464.04   306.8     463   330.7  464.13   362.6  463.67
   374.5  462.85   394.4  459.53   398.6 459.374   402.4  459.07   433.6 459.923
   438.2  461.59   442.2  464.43   446.2  466.39     498  477.03   565.9  497.27
   617.8  515.67   657.8  526.27   709.7  535.78   749.7  542.02   849.5  554.18
#Mann= 3 ,-1 , 0
       0     .12       0   398.6    .045       0   433.6     .12       0
Bank Sta=398.6,433.6
XS Rating Curve= 0 ,0
Exp/Cntr=0.3,0.1

Type RM Length L Ch R = 1 ,12424.1 ,317.5,318.5,319.3
XS GIS Cut Line= 3
     2384016.255      303309.884     2383998.995      303094.887
     2383634.485      302545.073
#Sta/Elev= 30
       0  550.26    47.9  544.52    91.9  537.82   127.8  531.35   203.7   514.8
   215.7  512.99   259.7  499.32   295.6  485.14   307.6  478.52   319.6  469.64
   331.6  464.17   339.6  462.95   379.6  461.58   387.6  458.55   391.6  457.12
   403.6  456.47   423.6  458.72   439.6  460.68   459.6  461.28   507.5  460.13
   523.5  466.22   567.5  476.81   591.5  484.98   623.5  497.49   663.5  510.77
   703.4  522.81   715.4  524.35   779.4  539.23   827.4   548.5   875.4   555.5
#Mann= 3 ,-1 , 0
       0     .12       0   387.6    .045       0   423.6     .12       0
Bank Sta=387.6,423.6
XS Rating Curve= 0 ,0
Exp/Cntr=0.3,0.1

Type RM Length L Ch R = 1 ,12105.6 ,327.1,328.4,329.4
XS GIS Cut Line= 3
      2384125.19      303282.135     2384176.504      302901.139
     2383844.324       302420.26
#Sta/Elev= 30
       0  543.73    95.1  530.55   178.4  515.24   245.7  504.88   301.2   492.3
   313.1  488.57     329  481.74   368.6  479.57   384.4  475.31   404.3  473.62
   416.2  470.86   428.2  466.72   444.1  464.13     464  461.74   487.8  461.25
   515.6  462.89   559.4  462.34   563.4  461.98   571.3  458.62   575.3  457.37
   583.2  457.16   607.1  458.01   611.1  459.58     623  466.35   666.7  480.31
   710.5  492.14     778  508.32   837.7  519.74   925.2  535.09   968.9   538.9
#Mann= 3 ,-1 , 0
       0     .12       0   571.3    .045       0   607.1     .12       0
Bank Sta=571.3,607.1
XS Rating Curve= 0 ,0
Exp/Cntr=0.3,0.1

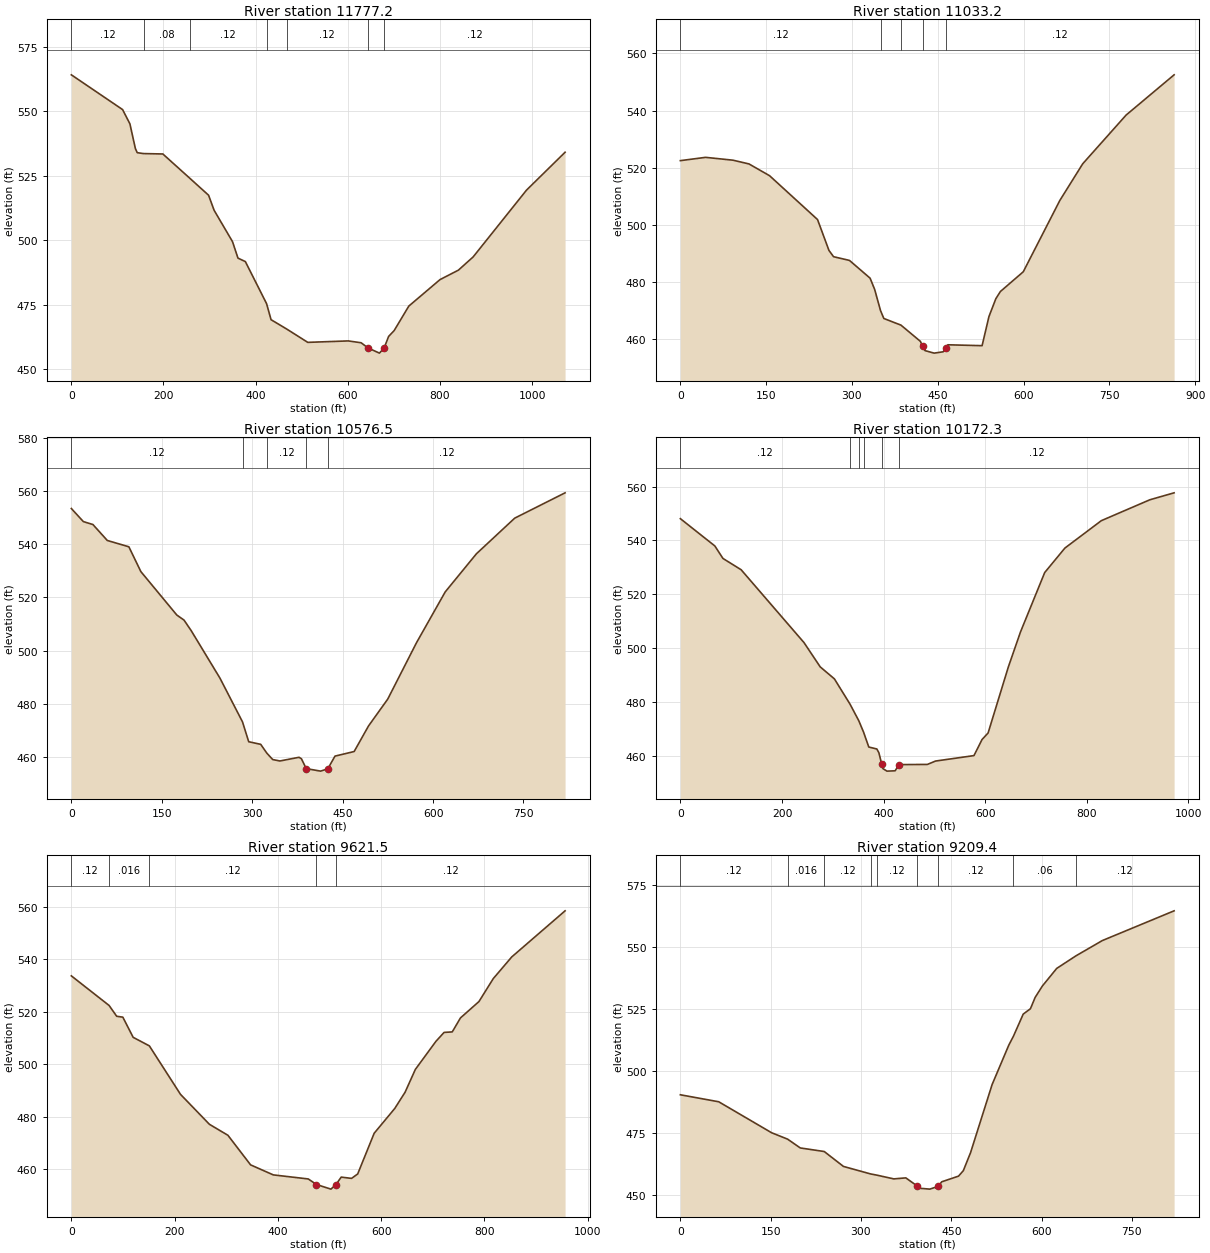
Type RM Length L Ch R = 1 ,11777.2 ,743.3,744,744.5
XS GIS Cut Line= 4
     2384801.294      302889.605     2384507.161      302842.137
     2384252.409      302427.748      2384307.01      302145.654
#Sta/Elev= 30
       0  564.04   111.2  550.58   127.1  545.06     139  535.47     143  533.88
  156.78533.5312   198.6  533.38  256.77524.0303   297.9  517.39   309.9  511.56
   349.8  499.42   361.7  493.03   377.7  491.69  423.76 475.394   433.5  469.18
  467.27465.5821   513.2   460.4     601  460.96   628.9  460.25     644  458.24
   668.7  456.23     679458.2507   688.7  462.71   700.6  464.94   732.5  474.45
   800.3  484.72   840.2  488.38   872.2  493.51   987.9  519.36  1071.7  534.05
#Mann= 7 ,-1 , 0
       0     .12       0  156.78     .08       0  256.77     .12       0
  423.76    .016       0  467.27     .12       0     644    .045       0
     679     .12       0
Bank Sta=644,679
XS Rating Curve= 0 ,0
Exp/Cntr=0.3,0.1

Type RM Length L Ch R = 1 ,11033.2 ,458.1,456.6,455.1
XS GIS Cut Line= 2
     2385133.027      302677.814     2384702.906      301929.385
#Sta/Elev= 30
       0  522.46      44  523.61    91.9  522.62   119.9  521.31   155.9  517.19
   239.8  501.83   259.8     491   267.8  488.82   295.7  487.51   331.7   481.3
   339.7  477.34  349.88 469.974   355.7  467.18  385.61464.8581   419.6  459.18
   423.6   457.4   427.6  455.94   443.6  455.05   459.6  455.52   463.6  456.96
   467.6  457.97   527.5  457.66   539.5  467.87   551.5  474.09   559.5  476.63
   599.5  483.54   663.4  508.51   703.4  521.35   779.3  538.42   863.2  552.51
#Mann= 5 ,-1 , 0
       0     .12       0  349.88    .016       0  385.61     .12       0
   423.6    .045       0   463.6     .12       0
Bank Sta=423.6,463.6
XS Rating Curve= 0 ,0
Exp/Cntr=0.3,0.1

Type RM Length L Ch R = 1 ,10576.5 ,403.5,404.2,405
XS GIS Cut Line= 3
     2385508.831      302382.207     2385281.681      302041.483
     2385053.918      301701.167
#Sta/Elev= 30
       0  553.47    19.9  548.55    35.8  547.44    59.6  541.44    95.4  539.06
   115.3  529.72   174.9  513.37   186.9  511.45   198.8  507.48   246.5   489.6
  283.92473.1172   294.2  465.65   314.1  464.67  324.14461.3929     334  458.94
   345.9   458.4   377.7  459.79   381.7  459.22   389.6  455.53   413.5  454.58
   425.4  455.45   437.3  460.23   469.1  461.96     493  471.61   524.8  481.69
   572.5  502.92   620.2  522.08   671.9  536.42   735.5  549.85     819  559.38
#Mann= 5 ,-1 , 0
       0     .12       0  283.92    .016       0  324.14     .12       0
   389.6    .045       0   425.4     .12       0
Bank Sta=389.6,425.4
XS Rating Curve= 0 ,0
Exp/Cntr=0.3,0.1

Type RM Length L Ch R = 1 ,10172.3 ,547.4,550.8,553.5
XS GIS Cut Line= 3
     2385663.573      302298.494     2385676.489      301959.765
     2385345.133      301420.714
#Sta/Elev= 30
       0  548.09    67.8  537.96    83.8  533.31   119.6  529.11   243.3  502.05
   275.2  493.03   303.1  488.58  333.82479.2058  351.06  473.06   360.6468.7513
   370.8  463.25   386.7  462.52   390.7  461.11  396.07 457.015   398.7  455.22
   406.6   454.3   422.6  454.42   430.5  456.72   486.2  456.79   502.1  458.04
   577.8  460.07   593.7  466.04   605.6  468.47   645.4  492.96   669.3  505.97
     717  528.07   756.8  537.17   828.5  547.35     924  555.11   971.7  557.69
#Mann= 6 ,-1 , 0
       0     .12       0  333.82     .06       0  351.06     .12       0
   360.6    .016       0  396.07    .045       0   430.5     .12       0
Bank Sta=396.07,430.5
XS Rating Curve= 0 ,0
Exp/Cntr=0.3,0.1

Type RM Length L Ch R = 1 ,9621.5  ,406.9,412.2,417.9
XS GIS Cut Line= 3
     2386173.904      301962.381     2385881.028       301386.27
     2385878.773      301076.423
#Sta/Elev= 30
       0  533.64   73.11522.3709    87.8  518.26    99.7  517.92   119.7  510.25
  151.05506.9979   211.4  488.54   267.3  477.16   303.2  472.97   347.1  461.71
     391   457.9   458.8  456.35   474.7  454.23   502.7  452.48  512.18 454.191
   522.6  457.05   542.6  456.57   554.5  458.25   586.4  473.74   626.3  483.18
   646.3  489.37   666.1  498.02   705.9   508.7   721.8  512.12   737.6  512.31
   753.5  517.63   789.3  523.86   817.1  532.61   852.8  540.84   956.1  558.39
#Mann= 5 ,-1 , 0
       0     .12       0   73.11    .016       0  151.05     .12       0
   474.7    .045       0  512.18     .12       0
Bank Sta=474.7,512.18
XS Rating Curve= 0 ,0
Exp/Cntr=0.3,0.1

Type RM Length L Ch R = 1 ,9209.4  ,452.6,450,447.7
XS GIS Cut Line= 3
     2386383.401      301714.383     2386285.479      301315.892
     2386195.679      300915.952
#Sta/Elev= 30
       0  490.47    63.7  487.65   151.4  475.17  178.15472.5574   199.2  469.01
  238.99467.5702   270.9  461.55  315.89458.5264  326.05458.0509   354.6  456.52
   374.5  456.93   392.8 453.764   398.4  452.72   414.3  452.39   427.8453.4662
   434.2  455.35   462.1  457.64     470  459.83     482  467.07   517.8  494.56
   545.6  510.52  553.26 514.093   569.5  523.02   581.5   525.2   589.4  529.79
   601.4  534.39   625.2  541.48  657.15546.5554   700.9  552.71   820.2  564.72
#Mann= 9 ,-1 , 0
       0     .12       0  178.15    .016       0  238.99     .12       0
  315.89     .06       0  326.05     .12       0   392.8    .045       0
   427.8     .12       0  553.26     .06       0  657.15     .12       0
Bank Sta=392.8,427.8
XS Rating Curve= 0 ,0
Exp/Cntr=0.3,0.1

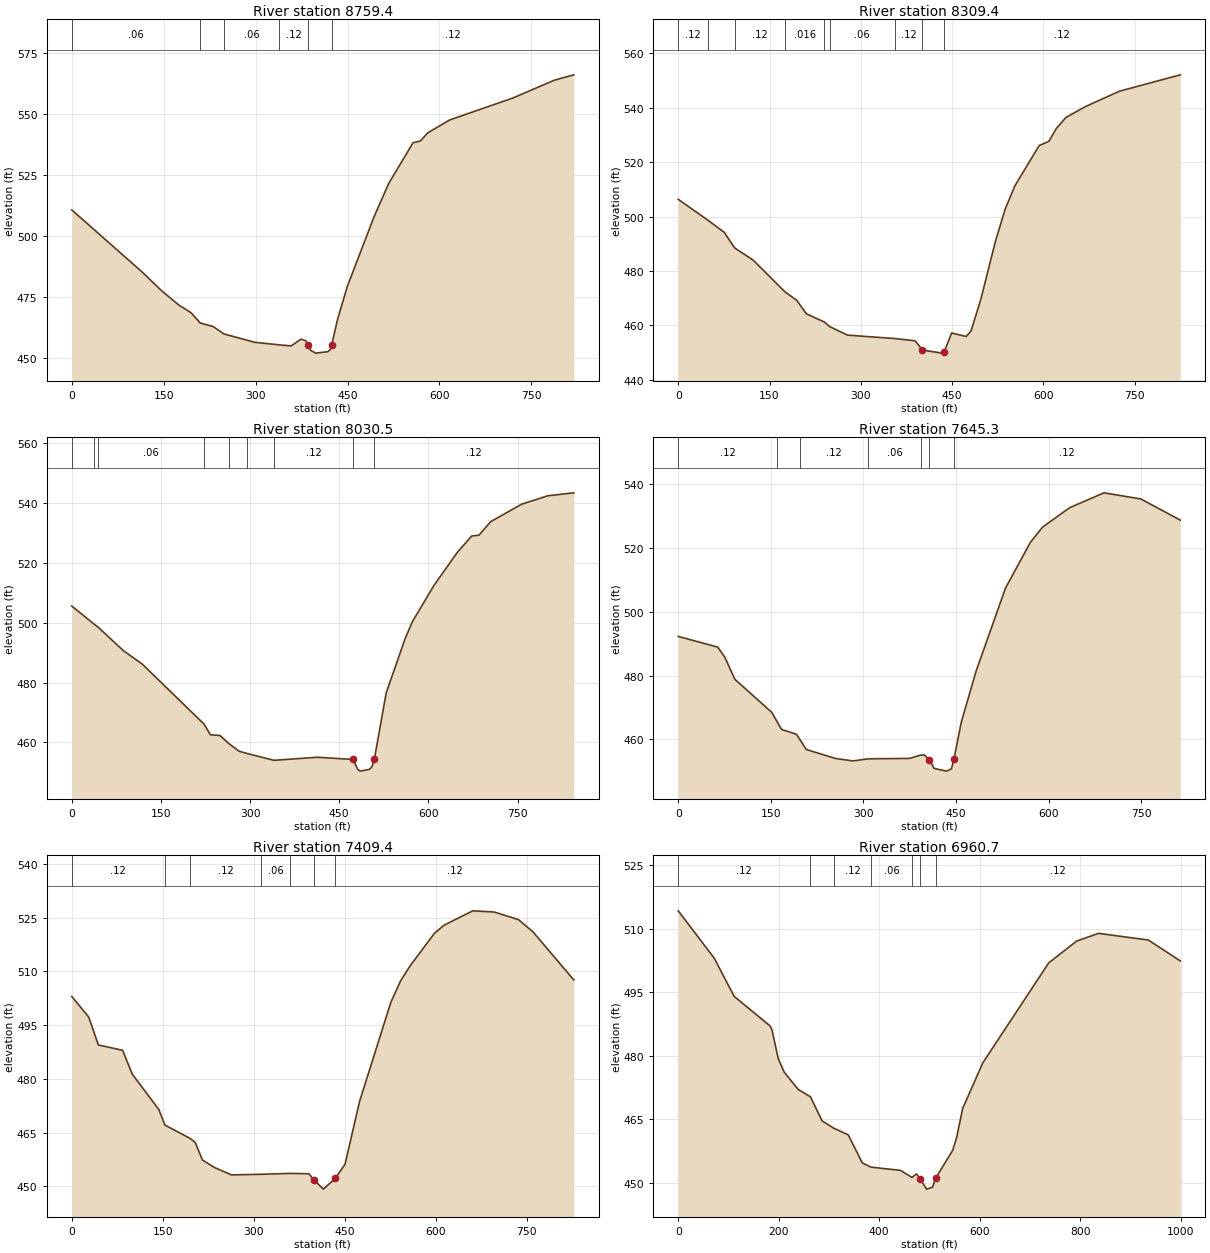
Type RM Length L Ch R = 1 ,8759.4  ,450.4,450,448.3
XS GIS Cut Line= 3
     2386823.813      301507.396     2386681.747      301122.946
     2386554.519      300733.779
#Sta/Elev= 30
       0  510.75   115.4  485.11   147.2  477.41   175.1   471.6     195  468.45
  209.58464.3074   230.8  462.83  248.28459.8033   298.4  456.38  337.72455.3348
   358.1  454.88     374  457.67     382  456.95     386  455.23     390  453.02
   397.9  451.92   417.8   452.5   421.8  453.41  424.27455.4354   433.7  465.77
   449.6  479.27   493.3  507.93   517.2  521.61   556.9  538.33   568.9  539.04
   580.8  542.38   616.6  547.68   719.9   556.7   787.5  564.02   819.3  566.22
#Mann= 6 ,-1 , 0
       0     .06       0  209.58    .016       0  248.28     .06       0
  337.72     .12       0     386    .045       0  424.27     .12       0
Bank Sta=386,424.27
XS Rating Curve= 0 ,0
Exp/Cntr=0.3,0.1

Type RM Length L Ch R = 1 ,8309.4  ,277.6,278.8,280.4
XS GIS Cut Line= 3
     2387247.947      301350.146     2387099.087      300964.652
     2386939.925       300584.92
#Sta/Elev= 30
       0  506.31   48.95498.6256    75.5   494.2   92.75488.4754   123.2  483.96
  175.39472.3185   194.7  469.21   210.6  464.25  240.13461.2202  248.96459.5274
   278.1  456.41  355.41455.1519   389.4  454.32   401.3  450.93   433.2  449.79
   437.2   450.3   449.2  457.18   473.2  455.92   481.2  457.97   497.2  469.56
   521.2  490.88   537.2   502.7   553.2   511.3   593.1  526.08   609.1  527.65
   621.1  532.32   637.1  536.42   669.1  540.41     725  546.06     825  552.08
#Mann= 9 ,-1 , 0
       0     .12       0   48.95     .06       0   92.75     .12       0
  175.39    .016       0  240.13     .12       0  248.96     .06       0
  355.41     .12       0   401.3    .045       0   437.2     .12       0
Bank Sta=401.3,437.2
XS Rating Curve= 0 ,0
Exp/Cntr=0.3,0.1

Type RM Length L Ch R = 1 ,8030.5  ,384.7,385.2,384.7
XS GIS Cut Line= 3
     2387408.211      301297.221     2387412.552      301075.809
     2387213.195       300485.21
#Sta/Elev= 30
       0  505.56   36.98499.6261   44.43498.4889      87  490.62   118.6  486.15
  222.55466.1035   233.4  462.52   249.4  462.29   264.1459.6143   281.4  457.05
  295.08456.2524  340.41453.9856   413.2     455   473.2  454.28   481.2  450.98
   485.2  450.37   501.2  450.98   505.2  451.88   509.2  454.43   529.1  476.57
   561.1  494.75   573.1  500.32     609  512.34     649  523.58     673     529
     685  529.24   704.9  533.78   756.9  539.62   800.8  542.43   844.8  543.42
#Mann= 9 ,-1 , 0
       0     .06       0   36.98     .12       0   44.43     .06       0
  222.55    .016       0   264.1     .12       0  295.08     .06       0
  340.41     .12       0   473.2    .045       0   509.2     .12       0
Bank Sta=473.2,509.2
XS Rating Curve= 0 ,0
Exp/Cntr=0.3,0.1

Type RM Length L Ch R = 1 ,7645.3  ,235.1,236,237.2
XS GIS Cut Line= 2
     2387740.905      301119.319     2387474.962      300350.953
#Sta/Elev= 30
       0  492.27    63.8  488.92    75.7  485.67    91.7  478.81   151.5  468.44
  159.23465.8046   167.4  463.07   191.3  461.59  197.45   459.8   207.3  456.79
   255.1  453.95     283  453.21  307.81453.8632   374.7  453.99  392.36 455.024
   398.6  455.08   406.5  453.61   414.5  450.84   434.4     450   442.4  450.73
   446.4  453.65   458.4  465.36   482.3  481.33   530.1  507.46     570   521.7
   589.9  526.54   633.7  532.64   689.5  537.32   749.3  535.39   813.1  528.75
#Mann= 7 ,-1 , 0
       0     .12       0  159.23    .016       0  197.45     .12       0
  307.81     .06       0  392.36     .12       0   406.5    .045       0
   446.4     .12       0
Bank Sta=406.5,446.4
XS Rating Curve= 0 ,0
Exp/Cntr=0.3,0.1

Type RM Length L Ch R = 1 ,7409.4  ,452.1,448.7,445.7
XS GIS Cut Line= 3
     2387927.481      301044.702     2387824.705      300646.829
     2387711.327      300245.628
#Sta/Elev= 30
       0  502.99    27.9  497.25    43.9  489.45    83.8  487.96    99.7  481.33
   143.6  471.42  153.67467.0916  194.44463.4319   203.5  462.28   215.4  457.35
   235.4  455.24   263.3  453.19  312.75453.3603  359.47453.6046     391  453.52
     399  451.81   414.9  449.22   434.8  452.26   450.6   456.2   474.5  473.68
   526.1  501.35     542   507.3   557.8   511.5   597.6  520.54   613.4  522.83
   661.1  526.88   696.8  526.54   736.5  524.42   760.4  521.02   827.8  507.59
#Mann= 7 ,-1 , 0
       0     .12       0  153.67    .016       0  194.44     .12       0
  312.75     .06       0  359.47     .12       0     399    .045       0
   434.8     .12       0
Bank Sta=399,434.8
XS Rating Curve= 0 ,0
Exp/Cntr=0.3,0.1

Type RM Length L Ch R = 1 ,6960.7  ,251.9,251.3,250.7
XS GIS Cut Line= 4
     2388254.934      300963.213     2388313.035        300682.8
     2388186.834      300384.444      2387831.92      300225.085
#Sta/Elev= 30
       0  514.22    71.6  503.05   111.4  494.01     183  487.02   186.9  485.99
   198.9  479.38   210.8  476.15   238.6  472.06  263.15470.2979   286.4  464.61
  309.91462.8612   338.4  461.31   366.4  454.68   383.5453.6885   442.3  452.92
  465.25451.2668   474.3  452.07  481.15450.9934   494.3  448.49   506.3  448.95
  512.22451.0572   546.3  457.65   554.3  460.76   566.3  467.58   606.3  478.32
   737.4  501.91   792.9  507.07   836.6   508.9   935.8  507.32   999.4  502.39
#Mann= 7 ,-1 , 0
       0     .12       0  263.15    .016       0  309.91     .12       0
   383.5     .06       0  465.25     .12       0  481.15    .045       0
  512.22     .12       0
Bank Sta=481.15,512.22
XS Rating Curve= 0 ,0
Exp/Cntr=0.3,0.1

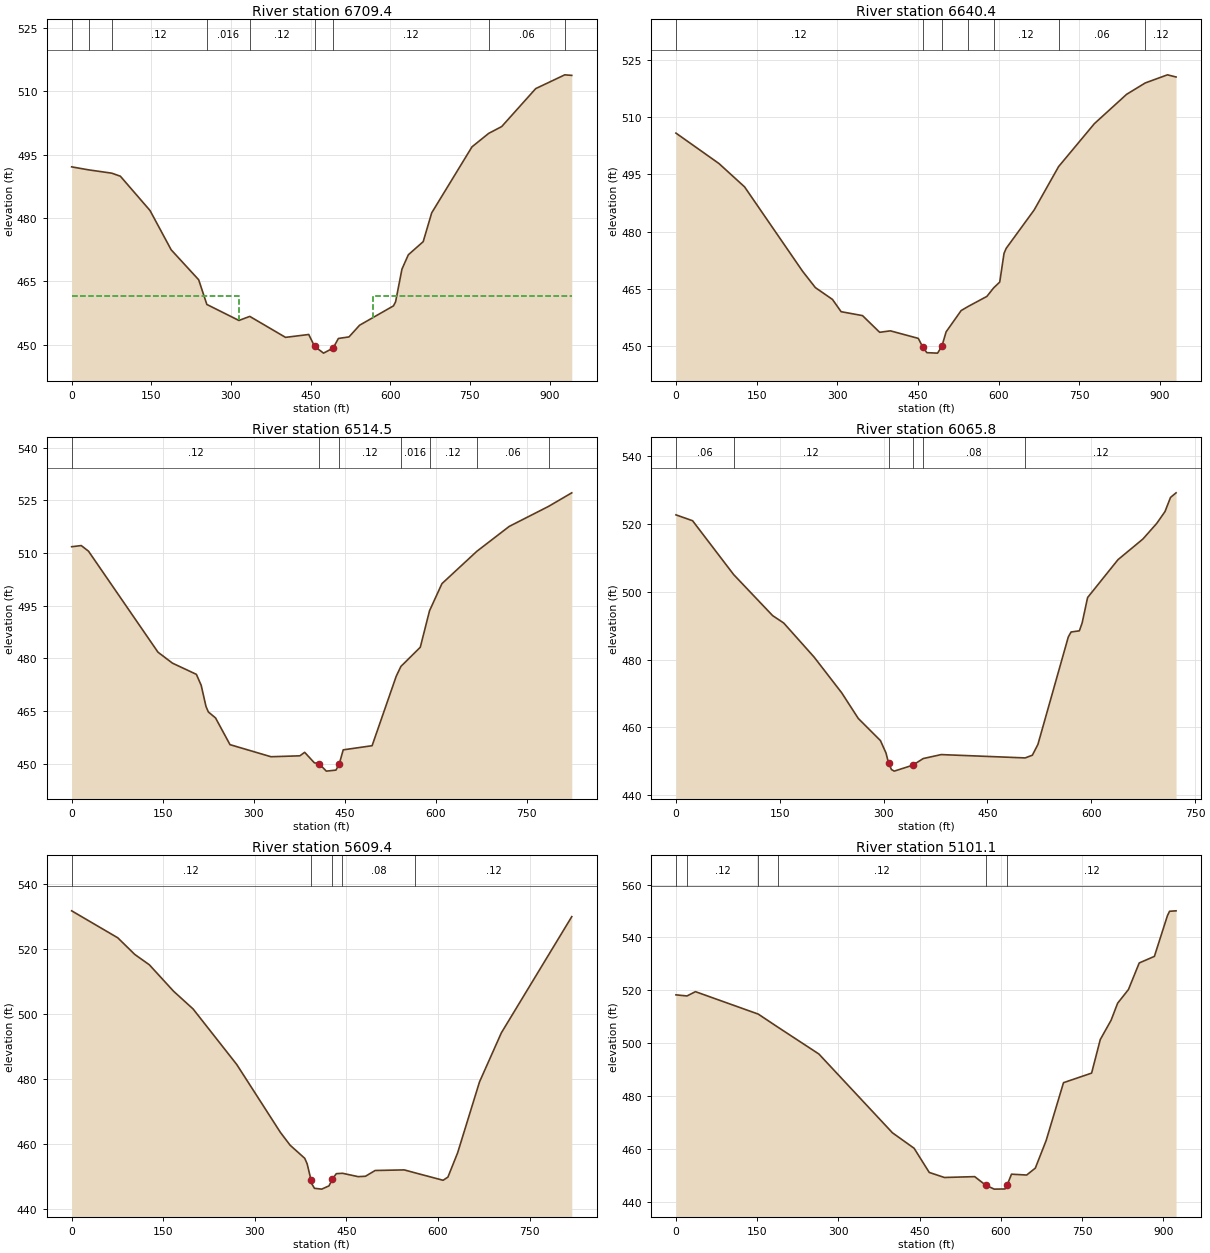
Type RM Length L Ch R = 1 ,6709.4  ,69,69,68.5
XS GIS Cut Line= 3
     2388630.493      300778.443     2388373.842      300220.686
     2388378.424       299892.85
#Sta/Elev= 30
       0  492.11   31.71491.4052   75.45490.6174    91.7   489.9   147.5  481.79
   187.4  472.48   239.2  465.39  254.59459.5472     315  455.76  335.39456.7239
   402.7  451.76   446.5  452.44   457.5449.6125   474.4  448.03   492.4  449.23
   502.3   451.5   522.3  451.87   542.2  454.63     606  459.21     610  460.17
     622  467.91     634   471.3     662  474.41     678  481.22   753.9  496.85
  785.36500.0349   809.9  501.65   873.9  510.63  928.66  513.89   941.8  513.76
#Mann= 9 ,-1 , 0
       0     .06       0   31.71     .08       0   75.45     .12       0
  254.59    .016       0  335.39     .12       0   457.5    .045       0
   492.4     .12       0  785.36     .06       0  928.66     .12       0
#XS Ineff= 2 , 0
          314.76  461.62  566.56          461.62
Permanent Ineff=
       F       F
Bank Sta=457.5,492.4
XS Rating Curve= 0 ,0
Exp/Cntr=0.3,0.1

Type RM Length L Ch R = 1 ,6640.4  ,126.3,125.8,125.8
XS GIS Cut Line= 4
     2388790.954       300648.85     2388567.507      300481.527
     2388431.669       300188.53     2388436.251      299860.694
#Sta/Elev= 30
       0  505.88    79.8   497.9   127.6  491.74   235.3  469.58   259.2  465.25
   291.1  462.13   307.1  458.91   346.9  457.88   378.8  453.49   398.8  453.87
   450.6  451.89   458.6  449.72   466.5  448.13   486.5  448.01   494.4  449.78
   502.4  453.61   530.3   459.2   543.4460.2885   578.2  462.93  590.68465.1568
   602.1   466.7   610.1  474.26   614.1  475.57   666.1  485.66  711.56497.0693
     778  508.35     838  516.08  872.79519.0787     914  521.21     930  520.64
#Mann= 7 ,-1 , 0
       0     .12       0   458.6    .045       0   494.4     .12       0
   543.4    .016       0  590.68     .12       0  711.56     .06       0
  872.79     .12       0
Bank Sta=458.6,494.4
XS Rating Curve= 0 ,0
Exp/Cntr=0.3,0.1

Type RM Length L Ch R = 1 ,6514.5  ,448.8,448.8,448.7
XS GIS Cut Line= 4
     2388852.945      300544.566     2388668.427      300402.066
     2388511.357      300072.512     2388514.328       299846.78
#Sta/Elev= 30
       0  511.77    15.8   512.1    27.7  510.51   142.2  481.74     166  478.62
   205.5  475.42   213.4  472.31   221.3  466.29   225.2  464.72   237.1     463
   260.9   455.4   328.4  451.96     376  452.22   383.9  453.22   399.8  450.24
   407.7  449.96   419.6  447.86   435.5  448.15  441.07450.0106   447.4  453.92
     495   455.1   534.7  474.86  542.45477.6781   574.4  483.14  589.66493.5472
   610.1  501.26  667.59510.4648     721  517.56  785.84523.2657     824  527.12
#Mann= 7 ,-1 , 0
       0     .12       0   407.7    .045       0  441.07     .12       0
  542.45    .016       0  589.66     .12       0  667.59     .06       0
  785.84     .12       0
Bank Sta=407.7,441.07
XS Rating Curve= 0 ,0
Exp/Cntr=0.3,0.1

Type RM Length L Ch R = 1 ,6065.8  ,455.8,456.4,457
XS GIS Cut Line= 2
     2389105.734      300418.647     2388796.896       299765.53
#Sta/Elev= 30
       0  522.69      24  520.96   83.37505.0694   139.7  492.96   155.7  490.78
   199.6  480.73   239.5  470.18   263.4  462.63   295.4   456.1   303.4  452.47
   307.1 449.529   311.3  447.57   315.3  447.09   342.1 448.839  357.16450.7966
   383.2  451.97  504.52450.9886   514.9  451.79   522.9  454.96   566.8  486.66
   570.8  488.13   582.8  488.48   586.8  490.79   594.7   498.3   638.6  509.47
   674.6  515.56   694.5  520.15   706.5  523.65   714.5  527.83   722.5  529.19
#Mann= 6 ,-1 , 0
       0     .06       0   83.37     .12       0   307.1    .045       0
   342.1     .12       0  357.16     .08       0  504.52     .12       0
Bank Sta=307.1,342.1
XS Rating Curve= 0 ,0
Exp/Cntr=0.3,0.1

Type RM Length L Ch R = 1 ,5609.4  ,506.3,508.2,509.7
XS GIS Cut Line= 3
     2389540.657      300301.253     2389374.343      299927.047
      2389208.03      299552.841
#Sta/Elev= 30
       0  531.75    75.5  523.46   103.4  518.34   127.2  515.17     167  507.02
   198.8   501.6   270.4  484.51   341.9  463.64   357.8  459.71   381.7  455.69
   385.6  454.01     392 449.052   393.6  447.76   397.6  446.47   409.5  446.22
   421.4  447.22     427 449.304   433.4  450.97  443.45451.0933   469.1  450.06
   481.1  450.17     497  451.95   544.7  452.13  562.36451.2288   608.3  448.94
   616.2  449.92   632.1  457.39   667.9  479.17   703.7  494.26     819  529.96
#Mann= 5 ,-1 , 0
       0     .12       0     392    .045       0     427     .12       0
  443.45     .08       0  562.36     .12       0
Bank Sta=392,427
XS Rating Curve= 0 ,0
Exp/Cntr=0.3,0.1

Type RM Length L Ch R = 1 ,5101.1  ,516.3,515.7,515
XS GIS Cut Line= 2
     2389960.789      300173.047     2389632.605      299310.172
#Sta/Elev= 30
       0  518.27   20.35517.8525      36  519.48  151.98510.9792  187.73506.0921
   263.8  495.88   399.6  466.04   439.6  460.18   467.6  451.02   495.6  449.11
   551.5  449.43   571.5  446.24   587.5   444.7   607.5  444.76   611.5  446.28
   619.4  450.36   647.4  450.04   663.4  452.66   683.4  463.12   715.4  485.01
   767.3  488.64   783.3  501.35   803.3  508.66   815.3   515.1   835.3  520.28
   855.2  530.35   883.2  532.84   907.2  548.22   911.2  549.92   923.2  550.09
#Mann= 6 ,-1 , 0
       0    .016       0   20.35     .12       0  151.98     .06       0
  187.73     .12       0   571.5    .045       0   611.5     .12       0
Bank Sta=571.5,611.5
XS Rating Curve= 0 ,0
Exp/Cntr=0.3,0.1