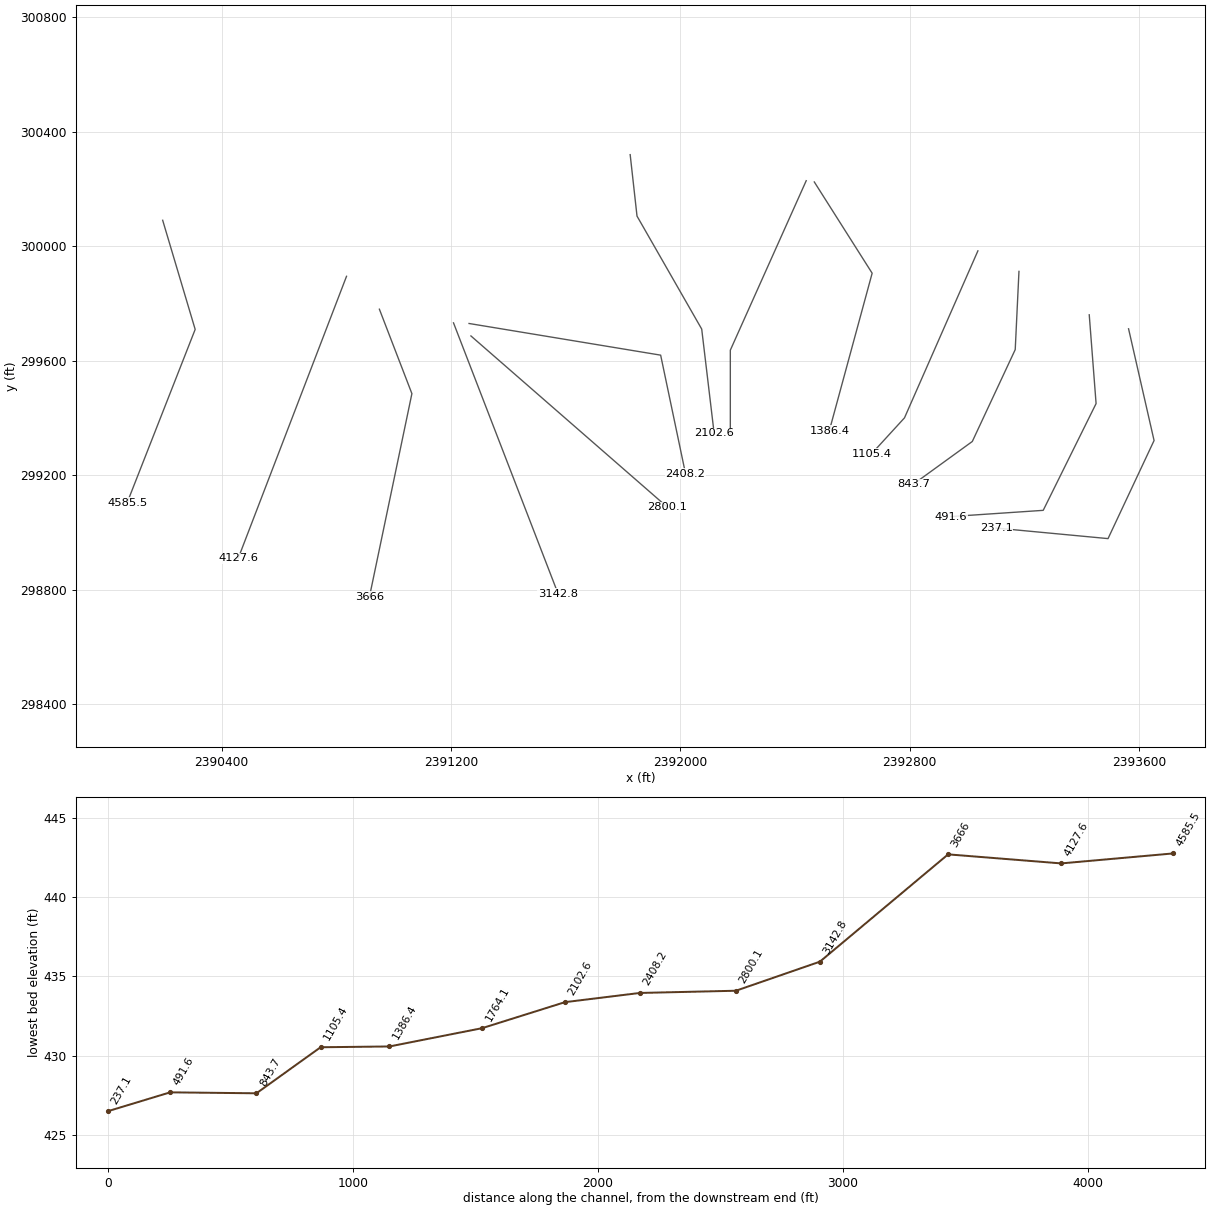
HEC-RAS study MILLCREEK2.prj: MILLCREEK2

--- MILLCREEK2.g01 (geometry) --- (continued)

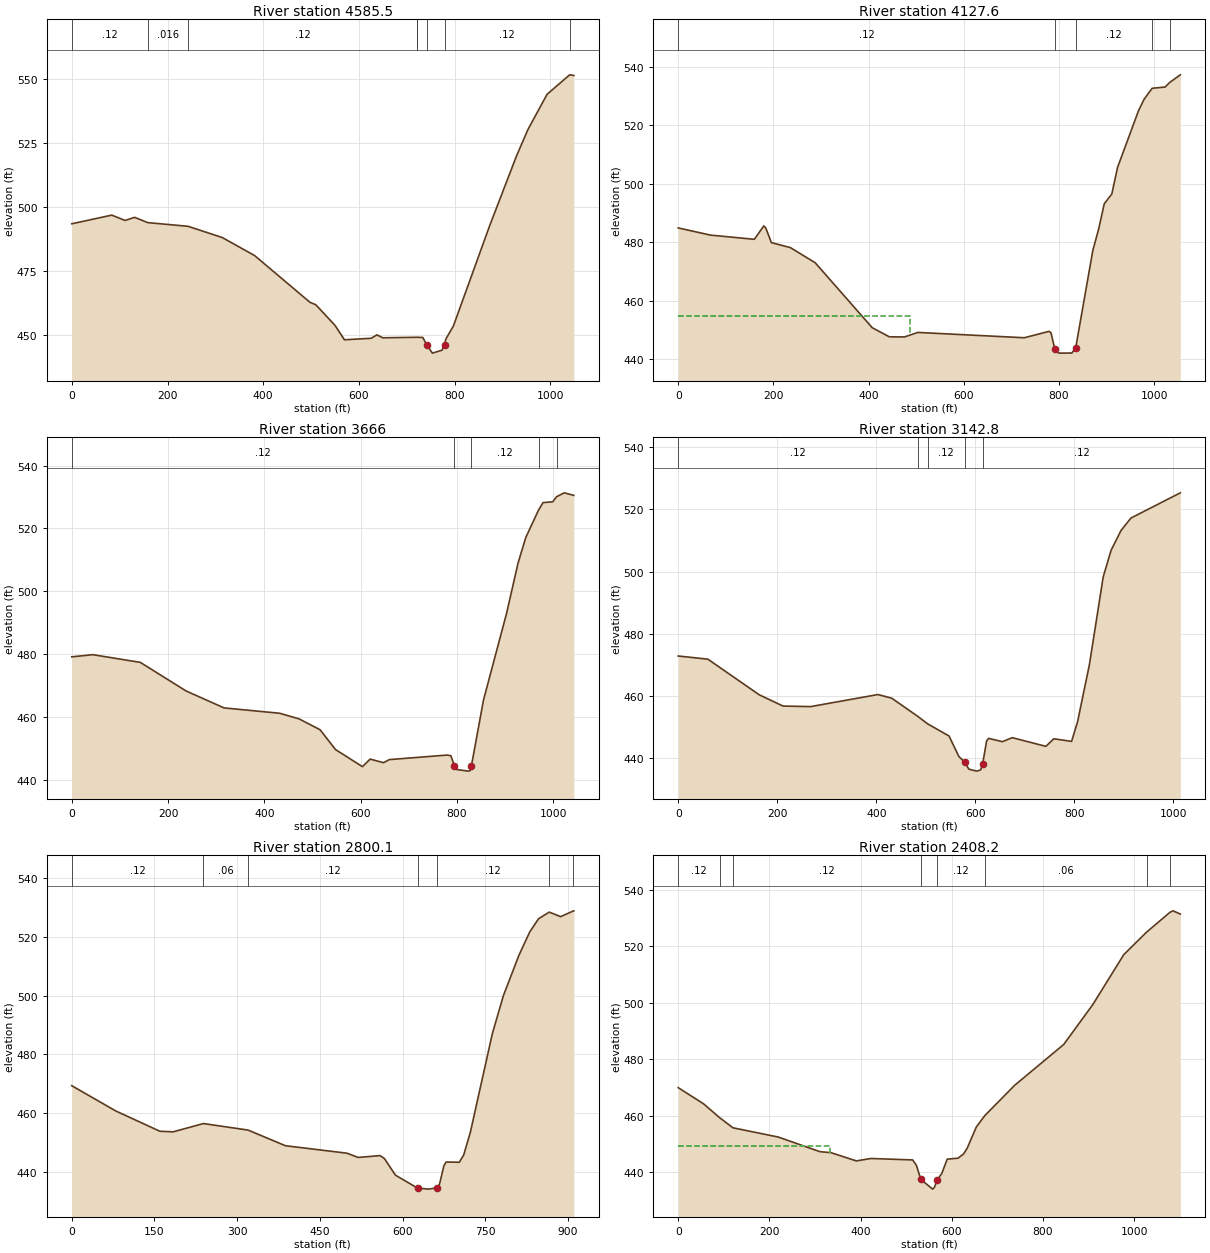
Type RM Length L Ch R = 1 ,4585.5  ,457.2,457.9,458.4
XS GIS Cut Line= 3
     2390194.299       300090.83     2390307.671      299709.295
     2390070.315      299103.232
#Sta/Elev= 30
       0  493.28    83.6  496.66   111.4  494.58   131.4   495.8  158.69 493.738
  242.98492.2914   314.4  487.91   382.1  480.85   497.8  462.58   509.8  461.66
   549.8  453.63   569.7  447.96   625.6  448.56   637.6  449.89   649.6  448.74
  720.88448.9407  721.53448.9502   733.4  448.86   741.4  446.01   753.4  442.75
   773.4  443.88  778.81 446.015   781.4  448.21   797.3  453.37   873.2   492.6
   929.1  519.77   953.1  530.14     993  543.86 1040.13 551.471  1048.9  551.22
#Mann= 8 ,-1 , 0
       0     .12       0  158.69    .016       0  242.98     .12       0
  720.88     .06       0  721.53     .12       0   741.4    .045       0
  778.81     .12       0 1040.13    .016       0
Bank Sta=741.4,778.81
XS Rating Curve= 0 ,0
Exp/Cntr=0.3,0.1

Type RM Length L Ch R = 1 ,4127.6  ,458.4,461.6,464.9
XS GIS Cut Line= 2
      2390835.67      299894.912     2390458.066      298909.669
#Sta/Elev= 30
       0  484.94    67.9  482.48   159.9  481.05   179.8  485.62   183.8  484.98
   195.8  479.91   235.8   478.2   287.8  473.03   407.7  450.81   443.6   447.7
   475.6  447.66   503.6   449.2   727.4  447.38   779.4  449.58   783.4  449.05
   791.3  443.59   799.3  442.12   827.3  442.15   835.3  443.96   871.3  477.27
   883.3  484.42   895.3   493.2   911.2  496.57   923.2  505.62   967.2     525
   979.2  529.01  995.86532.6881  1023.2  533.13 1032.55534.6556  1055.1   537.3
#Mann= 5 ,-1 , 0
       0     .12       0   791.3    .045       0   835.3     .12       0
  995.86    .016       0 1032.55     .06       0
#XS Ineff= 2 , 0
          487.93  454.86
Permanent Ineff=
       F       F
Bank Sta=791.3,835.3
XS Rating Curve= 0 ,0
Exp/Cntr=0.3,0.1

Type RM Length L Ch R = 1 ,3666    ,509.7,523.2,536
XS GIS Cut Line= 3
     2390950.339      299779.937     2391063.763      299484.769
     2390915.467      298773.581
#Sta/Elev= 30
       0  479.07    43.5  479.77   142.3  477.32   237.2  468.23   316.2  462.82
     432  461.11   471.9  459.34   515.8  455.85   547.7  449.56   603.6  444.12
   619.6  446.52   647.5  445.38   659.5  446.36   779.2   447.8   787.2  447.61
   794.8 444.441   799.2  443.21   823.2  442.69   827.2  442.81   829.8  444.21
   855.1  465.35     903  492.92   926.9  508.97   942.9  517.07  969.43525.8251
   978.8  528.19   998.8  528.44  1006.9530.0652  1022.7   531.3  1042.7  530.49
#Mann= 5 ,-1 , 0
       0     .12       0   794.8    .045       0   829.8     .12       0
  969.43    .016       0  1006.9     .12       0
Bank Sta=794.8,829.8
XS Rating Curve= 0 ,0
Exp/Cntr=0.3,0.1

Type RM Length L Ch R = 1 ,3142.8  ,331.7,342.7,353.7
XS GIS Cut Line= 2
     2391208.934      299732.152     2391573.518      298785.971
#Sta/Elev= 30
       0  472.91    59.9  471.89   163.7  460.44   211.6  456.83   267.5  456.66
   403.2  460.53   431.2  459.36  484.46453.4474  503.69  451.12   546.9  447.22
   566.9  440.59   578.8  438.81   586.8  436.57   602.8  435.93   610.8  436.33
   614.8  438.28   622.8  445.64   626.8  446.46   654.7  445.39   674.7  446.68
   742.5  443.89   758.5  446.32   794.4  445.48   806.4  451.71   830.4  470.13
   858.3  498.34   874.3  506.91   894.2  513.21   914.2  517.22    1014  525.33
#Mann= 5 ,-1 , 0
       0     .12       0  484.46     .06       0  503.69     .12       0
   578.8    .045       0   614.8     .12       0
Bank Sta=578.8,614.8
XS Rating Curve= 0 ,0
Exp/Cntr=0.3,0.1

Type RM Length L Ch R = 1 ,2800.1  ,379.1,392,404.7
XS GIS Cut Line= 2
     2391269.727      299686.434     2391955.491      299087.476
#Sta/Elev= 30
       0  469.31    79.9   460.7   159.7  453.81   183.7   453.6  238.84456.4229
  319.73454.2016   387.4  448.88   499.2  446.33   519.2  444.89   559.1  445.51
   567.1  444.49     587  438.85     627  434.46   646.9   434.1   662.9  434.58
   666.9  435.79   674.9  442.09   678.9  443.33   702.8  443.25   710.8  445.75
   722.8  453.43   762.8   487.1   782.7  499.95   810.7  513.62   830.6  521.69
   846.6  526.17  865.83528.4088   886.6  526.87  909.78528.8338   910.5  528.85
#Mann= 7 ,-1 , 0
       0     .12       0  238.84     .06       0  319.73     .12       0
     627    .045       0   662.9     .12       0  865.83    .016       0
  909.78     .06       0
Bank Sta=627,662.9
XS Rating Curve= 0 ,0
Exp/Cntr=0.3,0.1

Type RM Length L Ch R = 1 ,2408.2  ,326,305.6,285.3
XS GIS Cut Line= 3
     2391263.188      299729.982     2391931.591      299619.304
     2392018.396      299204.808
#Sta/Elev= 30
       0  469.89    55.8  464.14   90.64 459.279  119.97455.6758   219.2  452.41
   310.8  447.22   334.8  446.88   390.6  443.95   422.4  444.81   514.1   444.3
   522.1  442.46  532.05437.4037   557.9  433.96   561.9  434.62  568.07437.2668
   577.9  439.48   589.8  444.57   613.7  444.92   625.7  446.42   633.7  448.47
   653.6  455.95  672.33 460.002   737.4  470.68   845.3  485.18   909.2  499.33
   977.1  517.01 1027.31525.0018 1078.72532.0348    1085  532.51    1101  531.37
#Mann= 8 ,-1 , 0
       0     .12       0   90.64     .06       0  119.97     .12       0
  532.05    .045       0  568.07     .12       0  672.33     .06       0
 1027.31     .12       0 1078.72    .016       0
#XS Ineff= 2 , 0
          331.89  449.19
Permanent Ineff=
       F       F
Bank Sta=532.05,568.07
XS Rating Curve= 0 ,0
Exp/Cntr=0.3,0.1

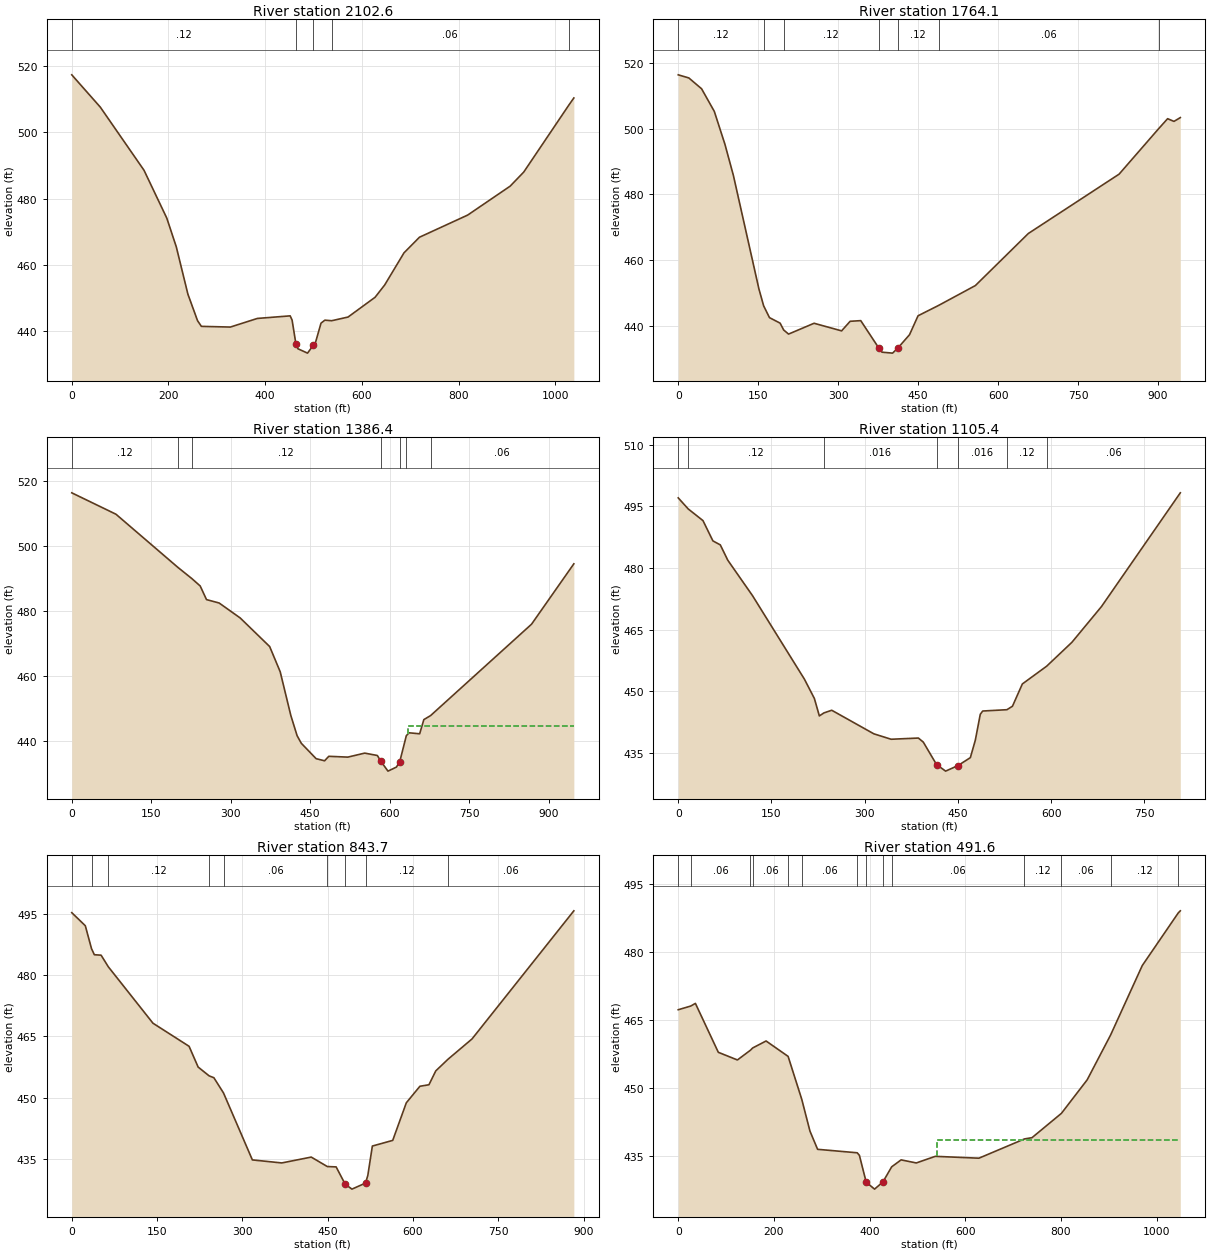
Type RM Length L Ch R = 1 ,2102.6  ,361.1,338.5,315.7
XS GIS Cut Line= 4
     2391825.254      300320.259     2391849.125      300105.416
      2392074.82       299710.45     2392118.222      299345.867
#Sta/Elev= 30
       0   517.3      59  507.56   149.4  488.52   196.5  474.09   216.2   465.4
   240.1  451.18   260.1  443.16     268  441.45   327.9  441.24   383.8  443.84
   451.6  444.62   455.6  443.34   463.6  436.05   467.6   434.7   487.5  433.38
   499.5  435.75   503.5  436.34   515.4  442.42   523.4  443.32   537.4  443.15
   571.3  444.26   627.2  450.22   647.1  453.94     687  463.62     719  468.33
   818.7  475.01   906.5  483.73   934.5  487.96 1027.86508.1711  1038.2  510.32
#Mann= 5 ,-1 , 0
       0     .12       0   463.6    .045       0   499.5     .12       0
   537.4     .06       0 1027.86     .12       0
Bank Sta=463.6,499.5
XS Rating Curve= 0 ,0
Exp/Cntr=0.3,0.1

Type RM Length L Ch R = 1 ,1764.1  ,374,377.6,381
XS GIS Cut Line= 3
     2392439.403      300229.114     2392174.646      299636.666
     2392174.646      299343.697
#Sta/Elev= 30
       0  516.37    19.9  515.42    43.8  512.13    67.7  505.24    87.6  495.25
   103.5  485.76   151.3   451.3  160.22446.1247   171.2  442.53   191.1  440.86
  197.84438.7704     207  437.53   254.8  440.82   306.5  438.51   322.5  441.42
   342.4  441.62  376.31433.2861   382.2  432.03   402.1  431.74  411.89433.2586
   433.9  437.34   449.9   443.1  488.63446.2624   557.4  452.28   656.8  468.12
   827.1  486.17  901.77500.0867   918.1  503.03     930  502.21   941.9  503.36
#Mann= 7 ,-1 , 0
       0     .12       0  160.22    .016       0  197.84     .12       0
  376.31    .045       0  411.89     .12       0  488.63     .06       0
  901.77    .016       0
#XS Ineff= 2 , 0
                          634.67          443.99
Permanent Ineff=
       F       F
Bank Sta=376.31,411.89
XS Rating Curve= 0 ,0
Exp/Cntr=0.3,0.1

Type RM Length L Ch R = 1 ,1386.4  ,284.3,281,277.8
XS GIS Cut Line= 3
     2392467.615      300224.773     2392669.438      299905.763
     2392520.161       299355.56
#Sta/Elev= 30
       0  516.21    83.4  509.63  200.22493.2846  226.62489.8241   242.4  487.55
   254.3  483.36   278.2  482.31   317.9  477.71   373.5  468.92   393.4  461.15
   413.4  447.74   425.3  441.49   433.3  439.14   461.2  434.42   477.2  433.77
   485.1  435.15     521   434.9   552.9  436.13   576.8   435.4  582.95433.7099
   596.8  430.59   612.7  431.83  618.97433.4701  631.44 441.496   636.6  442.38
   656.6  442.08   664.5  446.44  677.25  447.68   867.8   475.8   947.6  494.37
#Mann= 7 ,-1 , 0
       0     .12       0  200.22    .016       0  226.62     .12       0
  582.95    .045       0  618.97     .12       0  631.44    .016       0
  677.25     .06       0
#XS Ineff= 2 , 0
                          634.67          444.49
Permanent Ineff=
       F       F
Bank Sta=582.95,618.97
XS Rating Curve= 0 ,0
Exp/Cntr=0.3,0.1

Type RM Length L Ch R = 1 ,1105.4  ,262.6,261.7,260.5
XS GIS Cut Line= 3
     2393038.361      299983.888     2392782.285       299400.12
     2392667.268      299274.252
#Sta/Elev= 30
       0  497.05   16.04494.3639    39.8  491.52    55.8  486.58    67.7  485.61
    79.7  481.89   119.5  473.26   203.2  452.89   219.1  448.22   227.1  443.98
  234.44444.7078     247  445.36   314.8  439.62   342.6   438.3   386.5  438.59
   394.4   437.6   415.7432.1433   430.3  430.54   450.2  431.89   470.1  433.82
   478.1  438.06   486.1  444.38     490  445.17  528.95445.4896   537.9  446.34
   553.8  451.76  592.95456.0853   633.5  461.89   681.1  470.59     808  498.28
#Mann= 7 ,-1 , 0
       0     .06       0   16.04     .12       0  234.44    .016       0
   415.7    .045       0   450.2    .016       0  528.95     .12       0
  592.95     .06       0
Bank Sta=415.7,450.2
XS Rating Curve= 0 ,0
Exp/Cntr=0.3,0.1

Type RM Length L Ch R = 1 ,843.7   ,352.9,352.1,351.3
XS GIS Cut Line= 4
     2393181.619      299912.129     2393168.599      299638.691
     2393018.859      299317.511     2392812.696      299167.771
#Sta/Elev= 30
       0  495.21    23.8  492.02   34.78486.3974    39.7  484.93    51.6  484.82
   64.21481.9926   142.8  468.19   206.3  462.55   222.2  457.48  241.48  455.33
   249.9  454.87  266.82451.1489   317.6  434.78   369.3  434.04   421.1  435.47
  449.38433.1608   464.9  433.07   480.8  428.84   492.7  427.64   516.6  429.12
   520.6  430.98   528.6  438.17   564.4  439.55   588.3  448.74   612.2  452.78
   628.1  453.15   640.1  456.54  661.82459.4093   703.8  464.34   882.9  495.66
#Mann= 9 ,-1 , 0
       0     .12       0   34.78    .016       0   64.21     .12       0
  241.48    .016       0  266.82     .06       0  449.38     .12       0
   480.8    .045       0   516.6     .12       0  661.82     .06       0
Bank Sta=480.8,516.6
XS Rating Curve= 0 ,0
Exp/Cntr=0.3,0.1

Type RM Length L Ch R = 1 ,491.6   ,254.2,254.6,254.9
XS GIS Cut Line= 4
     2393426.816      299760.364     2393450.688      299450.034
     2393266.226       299076.77     2392945.045      299055.068
#Sta/Elev= 30
       0  467.31   26.07468.1224    35.9  468.71    83.8  457.91   123.7  456.22
  151.04458.3812  155.54458.8636   183.6  460.41  229.67457.0111  258.25447.5186
   275.3  440.52   291.3  436.49  374.14 435.724   378.7  435.16   392.9429.2357
   410.4   427.7   427.9429.2935  446.14432.6232   465.9  434.16   497.6  433.48
   537.3  434.94   628.5  434.53  723.74438.7814   739.5  439.06  801.02444.4372
   854.8  451.83  903.72461.7152     970  477.07 1045.34488.7061  1049.5  489.15
#Mann= 14 ,-1 , 0
       0     .12       0   26.07     .06       0  151.04     .12       0
  155.54     .06       0  229.67     .12       0  258.25     .06       0
  374.14     .12       0   392.9    .045       0   427.9     .12       0
  446.14     .06       0  723.74     .12       0  801.02     .06       0
  903.72     .12       0 1045.34     .06       0
#XS Ineff= 2 , 0
                          539.94          438.45
Permanent Ineff=
       F       F
Bank Sta=392.9,427.9
XS Rating Curve= 0 ,0
Exp/Cntr=0.3,0.1

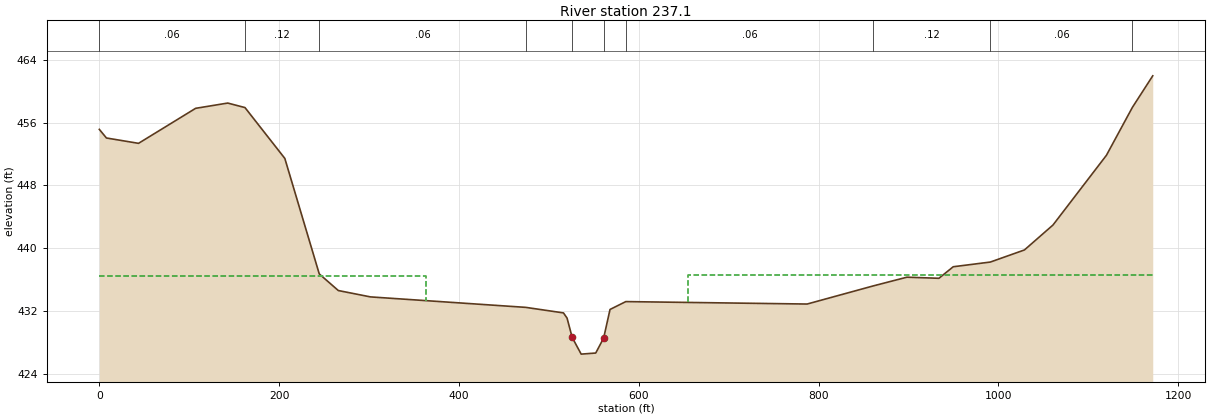
Type RM Length L Ch R = 1 ,237.1   ,229.8,237.1,244.3
XS GIS Cut Line= 4
     2393563.998      299711.463     2393652.974      299320.838
     2393492.383      298977.956     2393101.758      299014.848
#Sta/Elev= 30
       0  455.14     7.9  454.04    43.6  453.36   107.1  457.82   142.8  458.49
  161.98457.9161   206.3  451.44  244.61436.7242   265.8  434.61   301.5   433.8
  474.36432.4651   516.2  431.76   520.2   431.1   525.9428.6387   535.9  426.51
   552.1  426.65   560.9428.5598     568   432.2  585.57433.2018   787.2  432.89
  860.96435.2061   898.2  436.31   933.8  436.17   949.7  437.64  990.95438.2378
  1028.9  439.78  1060.6  442.95  1120.1  451.84 1148.98 457.943  1171.6  461.96
#Mann= 10 ,-1 , 0
       0     .06       0  161.98     .12       0  244.61     .06       0
  474.36     .12       0   525.9    .045       0   560.9     .12       0
  585.57     .06       0  860.96     .12       0  990.95     .06       0
 1148.98     .12       0
#XS Ineff= 2 , 0
          362.85  436.49  655.11          436.62
Permanent Ineff=
       F       F
Bank Sta=525.9,560.9
XS Rating Curve= 0 ,0
Exp/Cntr=0.3,0.1

Chan Stop Cuts=-1
Use User Specified Reach Order=0
Composite Channel Slope=5